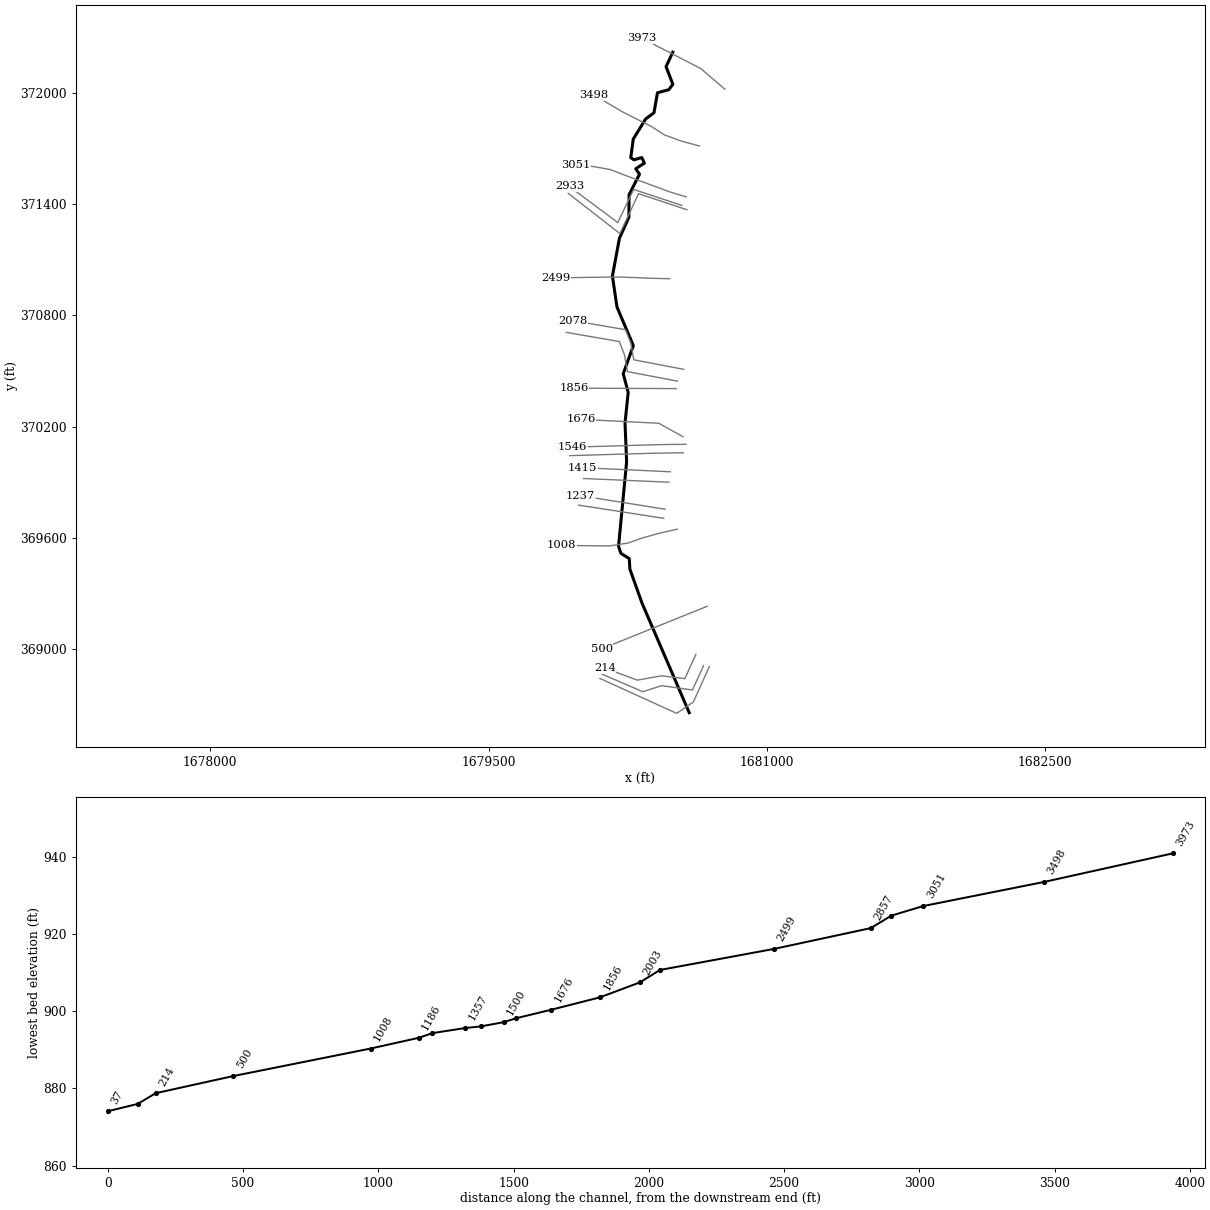
--- BUCKRN.prj (project) ---

Proj Title=BUCKRN
Current Plan=p01
Default Exp/Contr=0,0
English Units
Geom File=g01
Flow File=f01
Plan File=p01
BEGIN DESCRIPTION:
---------- MODELED AS PART OF WVEMD CTP PROGRAM, 2023----------
Stream Name: Buck Run
Flood Zone:  AFH
Wetzel County, WV
HEC-RAS Version: RAS 6.3
Vertical Datum: NAVD88
Projection: NAD 1983 StatePlane West Virginia S FIPS 4702 (US Feet)
Terrain: 1-meter West Virginia FEMA R3 South Central (collected 2018-2020)
Land Use: 2019 NLCD
Hydrologic Method:
WV 2010 Regional Regression Equations
Additional Model Notes:
None
END DESCRIPTION:
DSS Export Rating Curves= 0
DSS Export Rating Curve Sorted= 0
DSS Export Volume Flow Curves= 0
DXF OffsetX= 0
DXF OffsetY= 0
DXF ScaleX= 0
DXF ScaleY= 0

--- BUCKRN.p01 (plan) ---

Plan Title=Floodplain
Program Version=4.00
Geom File=g01
Flow File=f01
K Sum by GR=0
Std Step Tol=0.01
Critical Tol=0.01
Num of Std Step Trials=20
Max Error Tol=0.3
Flow Tol Ratio=0.001
Split Flow NTrial=30
Split Flow Tol=0.02
Split Flow Ratio=0.02
Log Output Level=0
Friction Slope Method=1
Unsteady Friction Slope Method=2
Unsteady Bridges Friction Slope Method=1
Global Log Level=0
CheckData=False
Run HTab=0
Run UNet=0
Run PostProcess=0
UNET Theta=0
UNET Theta Warmup=0
UNET ZTol=0
UNET ZSATol=0
UNET MxIter=0
UNET MaxInSteps=0
UNET DtIC=0
UNET DtMin=0
UNET MaxCRTS=0
UNET WFStab=0
UNET SFStab=0
UNET WFX=0
UNET SFX=0
UNET DSS MLevel=0
UNET DZMax Abort=0
UNET Convert EG Bridges=0
UNET Use Existing IB Tables=0
UNET Froude Limit=0
UNET Froude Power=0
Write IC File=0
Echo Input=False
Echo Output=False
Write Detailed=0

--- BUCKRN.f01 (steady flow) ---

Flow Title=Flow
Program Version=6.31
Number of Profiles= 1
Profile Names=F01pct
River Rch & RM=BUCKRN,Main            ,3973
     662
Boundary for River Rch & Prof#=BUCKRN,Main            , 1
Up Type= 0
Dn Type= 3
Dn Slope=0.02677
DSS Import GetInterval= 0
DSS Import GetPeak= 0
DSS Import FillOption= 0

--- BUCKRN.g01 (geometry) ---

Geom Title=Geometry
Program Version=6.31

River Reach=BUCKRN          ,Main
Reach XY= 30
     1680492.721      372221.714     1680456.376      372143.667
     1680493.104      372048.403     1680471.296      372019.327
     1680410.083      372002.493     1680391.336      371894.604
     1680346.574      371861.319      1680279.83      371752.833
       1680266.1      371651.899     1680283.541      371640.767
     1680325.845      371652.641     1680339.575      371622.583
     1680293.189      371592.526     1680313.228      371562.839
     1680257.194      371451.886     1680256.081      371330.542
     1680205.243      371217.362     1680167.392      371012.524
     1680191.884      370845.908     1680280.201      370636.989
     1680225.652      370485.587      1680252.37      370384.282
       1680235.3      370220.263     1680243.835      370009.489
     1680200.419      369553.429     1680213.035      369515.578
     1680258.308      369487.005     1680261.276      369430.971
     1680326.216      369248.399     1680581.172      368655.178

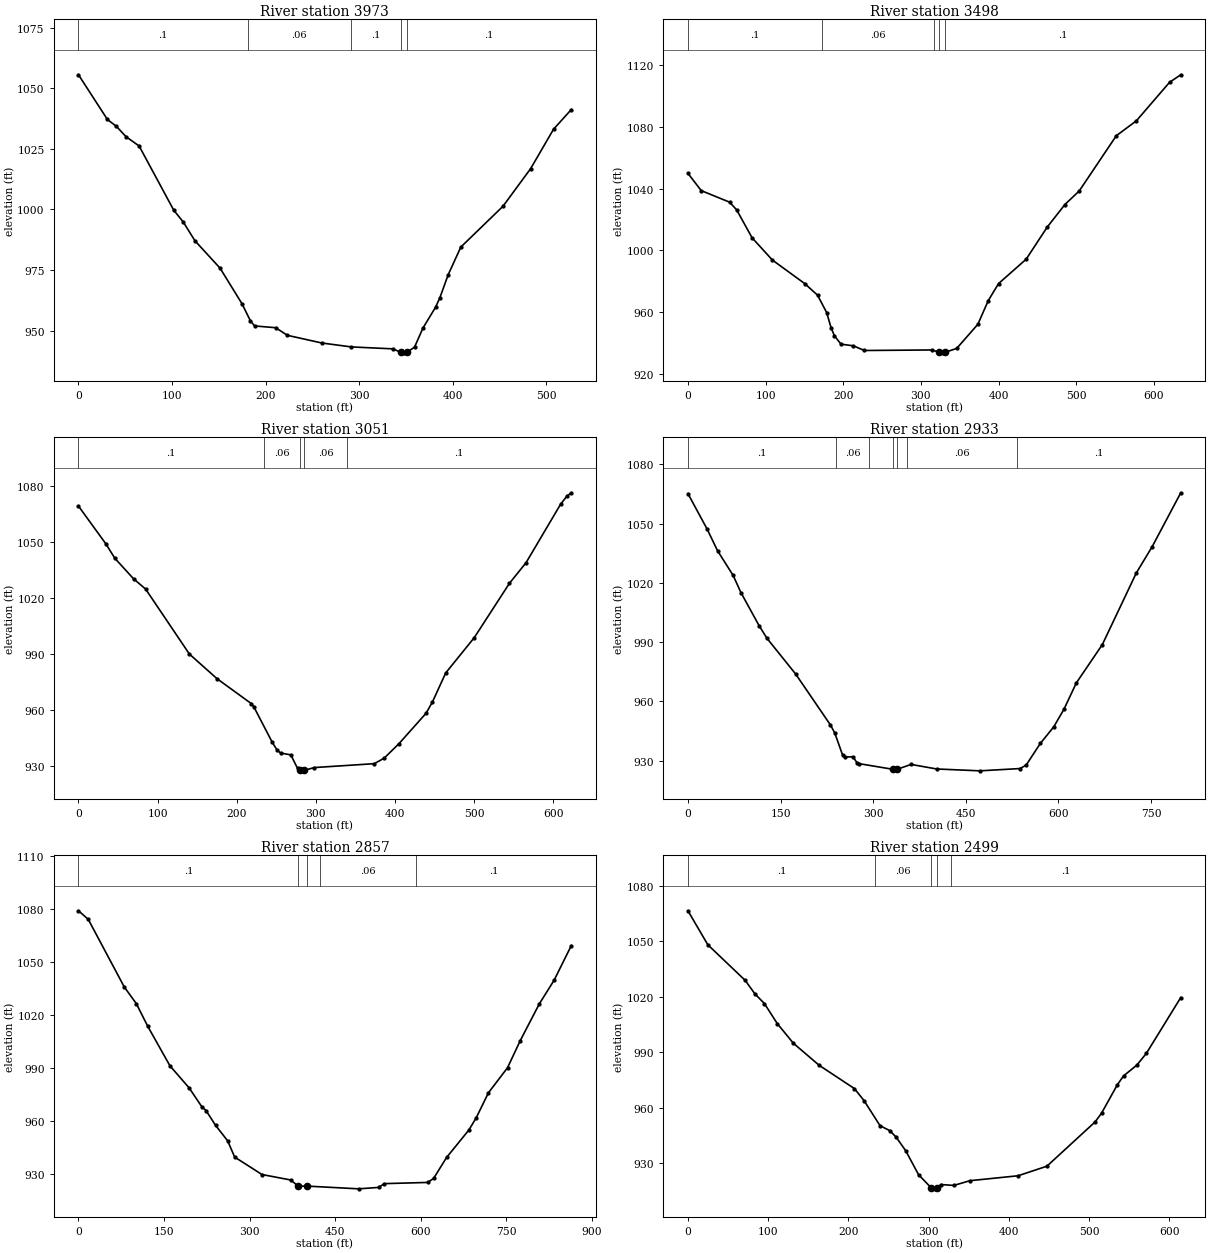
Type RM Length L Ch R = 1 ,3973    ,474.7,475.5,474
XS GIS Cut Line= 3
1680773.31869112372022.182499612 1680643.3736327372133.357716257
1680327.17399056372296.510956268
#Sta/Elev= 30
       0 1055.53    30.9  1037.1    40.5 1034.27    50.8 1030.02    64.8 1026.18
   101.8  999.72   112.1  994.78   124.5   987.1   151.3  975.83   174.7   961.2
   183.7  954.16   188.2     952   210.7  951.27   223.3  948.13   260.2  944.96
   291.7  943.35   336.1  942.55  344.42  941.14     348  940.91     351  941.14
   359.2  943.24   368.2  951.11   381.7  959.72   386.2  963.52   395.2  973.11
   408.7  984.51   453.7  1001.3   483.3 1016.82   507.8 1033.08526.8242 1041.21
#Mann= 5 ,-1,0
       0      .1       0  181.01     .06       0  291.01      .1       0
  344.42    .045       0     351      .1       0
Bank Sta=344.42,351
XS Rating Curve= 0 ,0
Exp/Cntr(USF)=0,0
Exp/Cntr=0.3,0.1

Type RM Length L Ch R = 1 ,3498    ,440.9,446.4,445.2
XS GIS Cut Line= 6
1680635.79509225 371715.181408511680537.39732318371742.206945002
1680446.71640217371775.4375215921680380.72276776371818.605742335
1680224.51507492371898.0274995121680067.81788176371990.275674582
#Sta/Elev= 30
       0 1049.83    17.1 1038.64    53.6 1031.15    62.7 1026.18    82.6 1008.05
   108.8  993.61   150.3  978.42   166.9  970.87   178.6  959.63   184.4  949.66
   188.6  944.59   197.1  939.11   212.9  938.07   227.3  935.03   314.4  935.38
   323.7  933.86     328  933.51  331.16  933.86   346.1  936.39   373.3  951.99
   386.7  967.34     400  978.41   435.5  994.18   462.4 1014.82   485.4 1029.63
   503.8 1038.37   551.6 1074.19   577.5  1083.9   620.2 1108.84634.6119  1113.7
#Mann= 5 ,-1,0
       0      .1       0  172.04     .06       0  317.48      .1       0
   323.7    .045       0  331.16      .1       0
Bank Sta=323.7,331.16
XS Rating Curve= 0 ,0
Exp/Cntr(USF)=0,0
Exp/Cntr=0.3,0.1

Type RM Length L Ch R = 1 ,3051    ,115.6,117.9,122.6
XS GIS Cut Line= 6
1680565.20769578 371440.16422942 1680473.5871441371468.219291416
1680227.20673136 371560.170223011680156.90405043371587.787621838
1680067.34943953371603.6461859171679970.41853103371613.732451838
#Sta/Elev= 30
       0  1069.2    34.6 1048.96      46  1041.2    69.6 1030.22    84.8 1024.73
   140.1   989.9   174.9  976.72   218.4  963.31   221.5  961.64   244.7  942.66
   251.2  938.21   255.6  936.77   268.3  935.85   276.8  928.57  279.67  927.55
   281.1  927.27   285.3  927.55   298.1  929.03   373.8  931.11   386.2  934.06
   405.1   941.9   439.2  958.15   447.3  964.25     464  979.75   500.1  998.69
   544.6 1027.85   565.5 1038.84   609.2 1070.22     617 1074.46622.7349 1076.35
#Mann= 5 ,-1,0
       0      .1       0   233.8     .06       0  279.67    .045       0
   285.3     .06       0   338.8      .1       0
Bank Sta=279.67,285.3
XS Rating Curve= 0 ,0
Exp/Cntr(USF)=0,0
Exp/Cntr=0.3,0.1

Type RM Length L Ch R = 1 ,2933    ,71.7,76.4,80.1
XS GIS Cut Line= 4
1680541.58333694371394.1147172681680281.69322011371480.744756212
1680196.50701515371301.7093423941679935.31744773 371496.48254662
#Sta/Elev= 30
       0  1065.2    31.1 1047.22    47.9 1036.29    73.2 1023.76    85.9 1015.02
   115.4  998.21     128   991.9   174.4  973.82   230.8     948   237.7  943.99
   250.3  932.87   254.5   931.8   267.2  931.91   273.9   928.8   277.6  928.39
   331.9  925.56   338.7  925.56   361.4  928.03   402.6  925.73   472.7  924.78
   537.6  925.94   547.6  927.66   570.6  938.67   592.5  947.14   608.9  956.02
   628.9  969.33     671  988.74     726 1025.02   751.8  1038.4     798 1065.64
#Mann= 7 ,-1,0
       0      .1       0     240     .06       0  293.95      .1       0
   331.9    .045       0   338.7      .1       0  353.95     .06       0
  532.22      .1       0
Bank Sta=331.9,338.7
XS Rating Curve= 0 ,0
Exp/Cntr(USF)=0,0
Exp/Cntr=0.3,0.1

Type RM Length L Ch R = 1 ,2857    ,363.6,357.5,349.3
XS GIS Cut Line= 4
1680568.29426562 371371.013373551680308.40414879371457.643412494
1680207.62453681 371242.22338232 1679929.5421118371459.087246476
#Sta/Elev= 30
       0 1079.19    17.1 1074.34    80.3 1035.99   101.4 1026.57   121.5 1013.68
   160.4  991.29   194.1  978.76   216.4  968.05   223.7  965.94   240.5  957.51
   261.6  948.77   273.9  939.56   321.8  929.67   372.3  926.56  385.25  923.09
   401.4  923.09   491.6  921.55   526.4  922.36   536.5   924.5   612.6  925.18
   622.8  927.44   645.6  939.33   684.7   954.9   697.7   961.9   719.1  976.04
   752.5   990.2   774.9 1005.64   808.2 1026.38   834.3 1039.87   864.4 1059.48
#Mann= 5 ,-1,0
       0      .1       0  385.25    .045       0   401.4      .1       0
  423.95     .06       0  591.78      .1       0
Bank Sta=385.25,401.4
XS Rating Curve= 0 ,0
Exp/Cntr(USF)=0,0
Exp/Cntr=0.3,0.1

Type RM Length L Ch R = 1 ,2499    ,421.6,421.2,414.9
XS GIS Cut Line= 6
1680475.48078033370998.5105977511680380.51115401371000.650357261
1680292.53232734371004.3868983391680217.47834359371007.341616839
1680117.47263809371006.9354496751679861.25300618371002.993856505
#Sta/Elev= 30
       0 1066.42    24.8 1048.04    71.4  1028.8    83.4 1021.57    95.3  1016.3
   111.4 1005.44   131.4  994.86   163.5  982.95   207.5  970.35   219.5  963.87
   239.5  950.27   251.5  947.65   259.5  944.13   271.5  936.75   287.5  923.81
  303.43  916.64   307.5  916.16   310.1  916.64   315.5  918.49   331.5     918
   351.5  920.56   411.5  923.22   447.5  928.39   507.6  952.32   515.6  957.02
   535.5   972.5   543.1  977.21   559.6     983   571.6  989.42614.4205 1019.54
#Mann= 5 ,-1,0
       0      .1       0  233.05     .06       0  303.43    .045       0
   310.1     .06       0  328.16      .1       0
Bank Sta=303.43,310.1
XS Rating Curve= 0 ,0
Exp/Cntr(USF)=0,0
Exp/Cntr=0.3,0.1

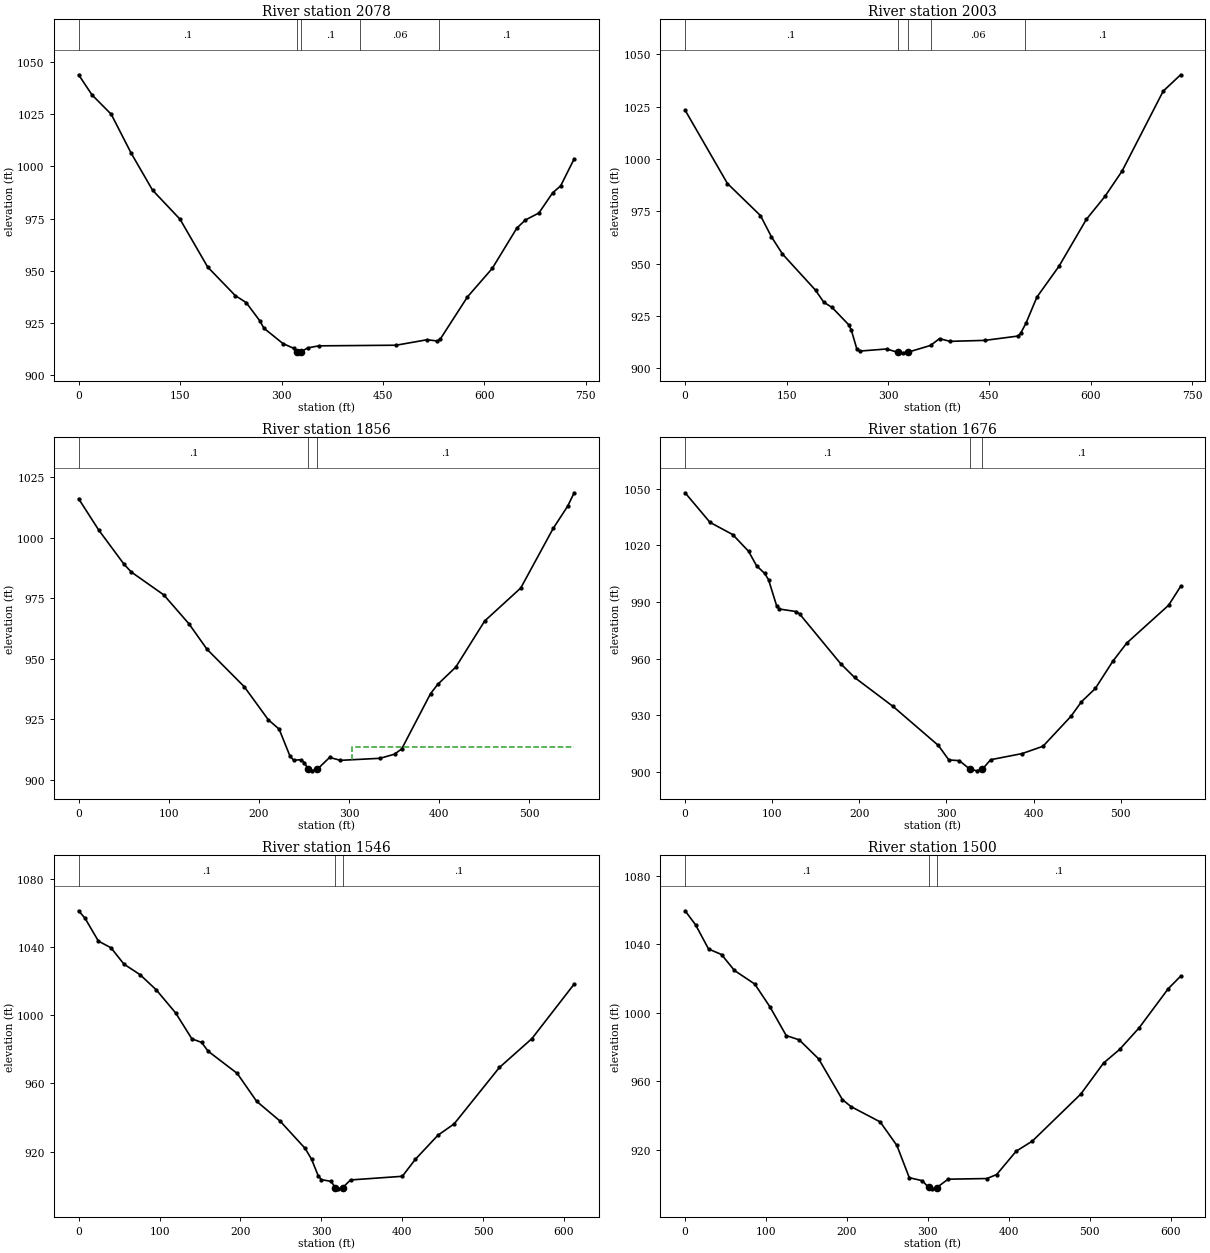
Type RM Length L Ch R = 1 ,2078    ,79.6,75.6,72.7
XS GIS Cut Line= 5
1680551.47359972370509.174431115 1680282.4873288370560.632674248
1680266.11425144370651.8541052561680238.04611882370723.193942326
1679952.68677054370772.313174408
#Sta/Elev= 30
       0 1043.93    19.7 1034.33    48.2 1025.02    77.5 1006.48   109.3  988.65
     150   974.7   190.8  951.83   231.6  938.15   247.8  934.78   268.1  925.97
   273.9  922.53   302.2  915.14   318.5  912.81   322.5  911.33   326.6  910.71
  329.25  911.33   338.8  913.08   355.2  914.06   469.5  914.36   515.3  916.99
   530.4  916.38   534.5  917.16     575  937.53   611.6  951.15   648.1  970.53
   660.7  974.37   680.6  977.71   700.9  987.36   712.7  990.67732.7621 1003.64
#Mann= 5 ,-1,0
       0      .1       0   322.5    .045       0  329.25      .1       0
  416.54     .06       0  533.21      .1       0
Bank Sta=322.5,329.25
XS Rating Curve= 0 ,0
Exp/Cntr(USF)=0,0
Exp/Cntr=0.3,0.1

Type RM Length L Ch R = 1 ,2003    ,139.5,146.8,153.9
XS GIS Cut Line= 5
1680517.55793948370445.4363799621680248.57166855370496.894623095
1680232.19859119370588.1160541031680204.13045858370659.455891173
1679918.77111029370708.575123255
#Sta/Elev= 30
       0 1023.34    62.6  988.32   111.4  973.03   127.7  962.86     144  954.64
   192.9  937.37   205.1  931.61   217.3  929.15   241.7  920.94   245.8  918.32
     254  909.24     258  908.29   298.1  909.31   314.1  907.72   321.7  907.46
   329.1  907.72   362.9  910.99   376.2  914.25   391.6  912.95   443.2  913.41
   491.9  915.46     496   916.7   504.1  921.64   520.3  934.13   552.8  948.77
   593.4  971.23   620.8  982.15   646.2  994.27     707 1032.45732.7621 1040.25
#Mann= 5 ,-1,0
       0      .1       0   314.1    .045       0   329.1      .1       0
  363.86     .06       0  503.21      .1       0
Bank Sta=314.1,329.1
XS Rating Curve= 0 ,0
Exp/Cntr(USF)=0,0
Exp/Cntr=0.3,0.1

Type RM Length L Ch R = 1 ,1856    ,180.3,180.1,180.1
XS GIS Cut Line= 2
1680510.54090632370405.0884393241679960.87330922370407.427450376
#Sta/Elev= 30
       0 1016.13    22.4 1003.13    50.4  989.03    58.4  985.84    94.4  976.39
   122.4   964.4   142.4  953.89   183.8  938.37   210.4  924.73   222.4  920.86
   234.4  909.74   238.4  908.04   246.4  908.17   250.4  906.99  254.73  904.28
   258.4  903.61   264.8  904.28   278.4  909.16   290.4  907.95   334.4   908.8
   350.4   910.5   358.4   912.7   390.4  935.56   398.4   939.4   418.4  946.53
   450.4  965.58   490.4  979.21   526.4 1003.87   542.4 1013.03549.6725  1018.6
#Mann= 3 ,-1,0
       0      .1       0  254.73    .045       0   264.8      .1       0
#XS Ineff= 2 , 0
                          303.67          913.49
Permanent Ineff=
       F       F
Bank Sta=254.73,264.8
XS Rating Curve= 0 ,0
Exp/Cntr(USF)=0,0
Exp/Cntr=0.3,0.1

Type RM Length L Ch R = 1 ,1676    ,129.8,130.1,131.3
XS GIS Cut Line= 3
1680547.96508314370145.4582126091680416.98046426370217.967555205
1679998.29748605370239.018654668
#Sta/Elev= 30
       0 1047.94    28.6 1032.24    54.7 1025.75    72.8 1016.94    82.1 1009.19
    91.3 1005.18    95.8 1001.83     105  988.11   108.1  986.27   127.8   984.9
   131.6  983.57   178.6  957.25   194.6  949.94   238.7  934.59   290.8  913.86
   302.8  906.18   314.8  905.81   326.8  901.34   334.8   900.4  341.42  901.34
   350.8   906.3   386.9  909.55   410.9  913.44     443  929.33     455  937.03
     471  944.12     491   958.5     507  968.18   555.1  988.26568.9268  998.26
#Mann= 3 ,-1,0
       0      .1       0   326.8    .045       0  341.42      .1       0
Bank Sta=326.8,341.42
XS Rating Curve= 0 ,0
Exp/Cntr(USF)=0,0
Exp/Cntr=0.3,0.1

Type RM Length L Ch R = 1 ,1546    ,45.5,45.5,45.5
XS GIS Cut Line= 6
1680564.08490884370104.2950088511680470.32098876370103.427228449
1680382.83953643 370101.511221781680207.91304901370096.441350026
1680132.94469501370094.2681260241679951.77051668370089.016824199
#Sta/Elev= 30
       0  1061.1       8 1056.67    24.4 1043.35      40 1039.42      56 1029.86
      76 1023.64      96 1014.74     120 1001.19     140  986.06     152  983.99
     160  978.86     196  965.83     220  949.49     249  937.89     280  921.86
     288  915.45     296  905.98     300  903.59   312.1  902.55   317.1  898.96
   320.1  898.19  326.49  898.96   336.1   903.4   400.1  905.54   416.1  915.43
   444.1  929.59   464.1  936.22   520.1  969.29   560.2  986.17612.5204 1018.16
#Mann= 3 ,-1,0
       0      .1       0   317.1    .045       0  326.49      .1       0
Bank Sta=317.1,326.49
XS Rating Curve= 0 ,0
Exp/Cntr(USF)=0,0
Exp/Cntr=0.3,0.1

Type RM Length L Ch R = 1 ,1500    ,85.3,84.9,84.5
XS GIS Cut Line= 6
 1680549.1466435370058.3641840821680455.38272342370057.496403679
1680367.90127109 370055.580397011680192.97478367370050.510525256
1680118.00642967370048.3373012541679936.83225134370043.085999429
#Sta/Elev= 30
       0 1059.66      13 1051.43      29 1037.32      45 1034.11      61 1024.78
    86.1 1016.85     105 1003.43     125  986.74     141  984.25   165.1  973.11
   194.4  949.34   205.1  945.23   241.1   936.3   261.8  922.52   277.1  903.71
   293.1  901.93   301.1  897.97   305.1  897.18  311.18  897.96   325.1  902.82
   373.1   903.2   385.1  905.54   409.2  919.16   429.2  925.08   489.2   952.6
   517.2  970.66   537.2  978.69   561.3  991.31   597.2 1014.13612.5204 1021.45
#Mann= 3 ,-1,0
       0      .1       0   301.1    .045       0  311.18      .1       0
Bank Sta=301.1,311.18
XS Rating Curve= 0 ,0
Exp/Cntr(USF)=0,0
Exp/Cntr=0.3,0.1

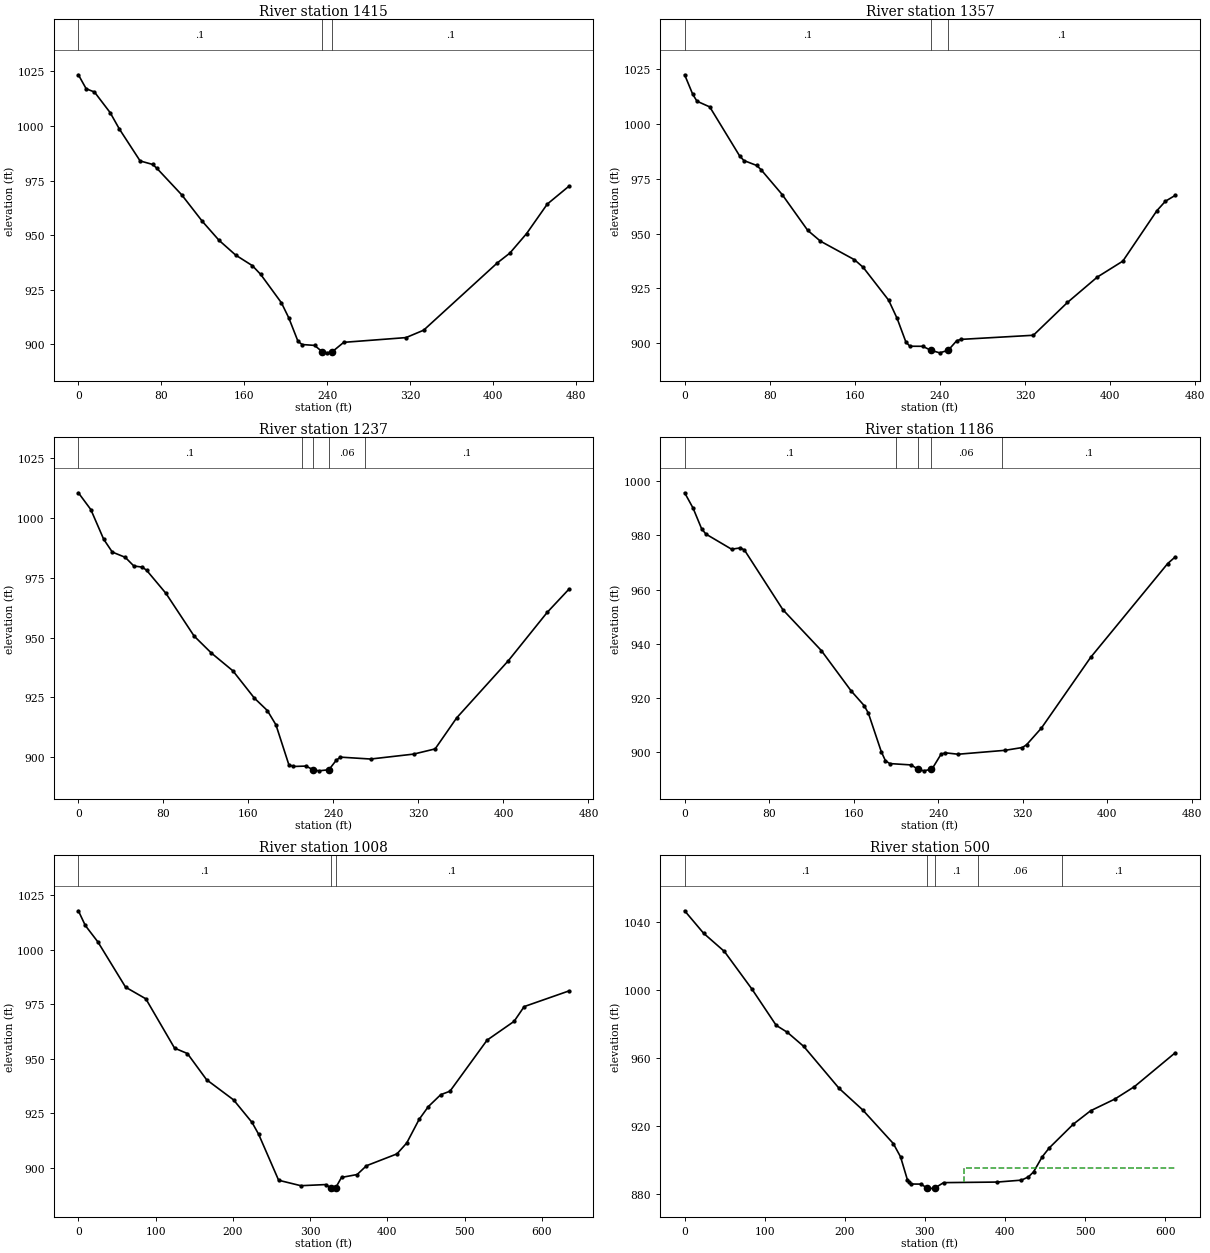
Type RM Length L Ch R = 1 ,1415    ,57.4,57.7,58.1
XS GIS Cut Line= 2
1680479.59579011369955.9819443611680007.27227145369978.148752096
#Sta/Elev= 30
       0 1023.46     7.5 1017.06    15.5 1015.56    30.6 1006.14    39.5  998.62
    59.5     984    71.6  982.38    75.6  980.65    99.6  968.47   119.6  956.25
   135.6  947.62   151.6  940.87   167.7  936.02   175.7  932.03   195.7  919.02
   202.8  912.12   211.7  901.34   215.7  899.89   227.7  899.49  234.94  896.61
   239.7  896.08   244.8  896.61   255.8  900.89   315.8  903.06   332.8  906.45
   403.9  937.31   415.9  941.76     432  950.68     452  964.23472.8434   972.4
#Mann= 3 ,-1,0
       0      .1       0  234.94    .045       0   244.8      .1       0
Bank Sta=234.94,244.8
XS Rating Curve= 0 ,0
Exp/Cntr(USF)=0,0
Exp/Cntr=0.3,0.1

Type RM Length L Ch R = 1 ,1357    ,121.5,120.8,119.7
XS GIS Cut Line= 2
1680471.71566188369899.8117634651680010.93048473369919.693357403
#Sta/Elev= 30
       0 1022.37     7.6 1013.48    11.6 1010.32    23.6 1007.73    51.6  985.47
    55.7  983.29    67.7  981.05    71.7   979.2    91.7  967.79   115.7  951.48
   127.7  946.54   159.7  938.08   167.8  934.66   191.8  919.65   199.8  911.32
     208  900.62   211.8  898.67   223.8  898.64  231.44  896.83   239.8  895.66
   247.8  896.83   255.8  901.18   259.8  901.79   327.9  903.67   359.9  918.61
     388  930.19     412  937.46     444  960.43     452  964.74461.2139   967.4
#Mann= 3 ,-1,0
       0      .1       0  231.44    .045       0   247.8      .1       0
Bank Sta=231.44,247.8
XS Rating Curve= 0 ,0
Exp/Cntr(USF)=0,0
Exp/Cntr=0.3,0.1

Type RM Length L Ch R = 1 ,1237    ,50.7,50.7,50.8
XS GIS Cut Line= 2
1680451.64647925369753.7404063491679995.86280944369826.635101016
#Sta/Elev= 30
       0 1010.44    11.7 1003.44    23.8  991.05    31.9  985.69    44.1  983.49
    52.2  979.87    60.3  979.39    64.3  978.03    82.4  968.44   108.9  950.62
   125.1  943.54   145.4   936.1   165.6  924.71   177.8  919.52   185.9  913.55
     198  896.96   202.1  896.16   214.2  896.33  220.79  894.81   226.4  894.34
  235.76  894.81   242.6  898.74   246.6  900.06     275  899.27   315.5  901.33
   335.7   903.5     356  916.48   404.6  940.33   441.1  960.48 461.576  970.18
#Mann= 5 ,-1,0
       0      .1       0     210     .06       0  220.79    .045       0
  235.76     .06       0     270      .1       0
Bank Sta=220.79,235.76
XS Rating Curve= 0 ,0
Exp/Cntr(USF)=0,0
Exp/Cntr=0.3,0.1

Type RM Length L Ch R = 1 ,1186    ,177.2,177.7,179.2
XS GIS Cut Line= 2
 1680443.9733535369704.6324015211679985.12043339369775.992471037
#Sta/Elev= 30
       0  995.74       8  990.06      16  982.52    20.1  980.51    44.4  974.92
    52.5  975.38    56.5  974.67      93  952.59   129.4  937.51   157.7  922.58
   169.9  917.22   173.9  914.43   186.1  900.25   190.1  896.82   194.2   895.8
   214.4   895.3  220.96  893.69   226.6  893.12  232.87  893.69   234.6  894.06
   242.7  899.24   246.8  899.77   258.9  899.25   303.5   900.7   319.7  901.73
   323.7  902.75   337.8  908.93   384.4  935.02   457.3  969.63464.3687  972.05
#Mann= 5 ,-1,0
       0      .1       0     200     .06       0  220.96    .045       0
  232.87     .06       0     300      .1       0
Bank Sta=220.96,232.87
XS Rating Curve= 0 ,0
Exp/Cntr(USF)=0,0
Exp/Cntr=0.3,0.1

Type RM Length L Ch R = 1 ,1008    ,507.5,508.3,508.4
XS GIS Cut Line= 6
1680517.21757351369646.1514258381680419.70070818369623.877520248
1680328.10902785369598.4845264261680250.68956326369570.942258671
 1680150.4387795369555.5059378451679894.20504001369558.384869084
#Sta/Elev= 30
       0 1017.89     8.9 1011.18    25.2 1003.63    61.1  982.85    87.3  977.51
   124.5  954.89   141.1  952.42     166  940.38   200.9  931.15   224.8   920.8
   233.3   915.4   259.2  894.29   287.9  891.79   320.3  892.31  326.54  890.78
   328.4  890.35   332.9  890.78   340.6  895.59   360.8  896.91   372.9  900.95
   412.4  906.39     425  911.38     441  922.18     453  928.08     469  933.53
     481  935.14     529  958.55     564  967.18     577  973.94634.9297  981.12
#Mann= 3 ,-1,0
       0      .1       0  326.54    .045       0   332.9      .1       0
Bank Sta=326.54,332.9
XS Rating Curve= 0 ,0
Exp/Cntr(USF)=0,0
Exp/Cntr=0.3,0.1

Type RM Length L Ch R = 1 ,500     ,287.8,286.4,282.8
XS GIS Cut Line= 6
1680678.05681875369229.6916288441680591.14032592369194.554560006
1680347.77499901369096.1705704181680278.24167351369068.061046585
1680197.11978851369035.2661646751680110.20395184369000.128111586
#Sta/Elev= 30
       0 1046.44    23.7 1033.23    49.6 1022.58    84.1 1000.42   114.3  979.19
   128.3  975.08   148.8  966.78   192.9  942.17   222.1  929.64   260.5  909.82
   269.6  901.97   278.2  888.41   280.6  886.98   282.5  886.04   295.5  885.99
  302.07  883.73   304.1  883.21   312.6  883.73   323.3  886.85   390.4  887.19
   420.6  888.32   429.2   890.2   435.6  893.11   446.5  902.03   455.1  907.15
   485.3  921.17   506.9  929.04   537.1   935.9   561.6   943.2   612.5  963.07
#Mann= 5 ,-1,0
       0      .1       0  302.07    .045       0   312.6      .1       0
  366.25     .06       0  471.25      .1       0
#XS Ineff= 2 , 0
                          349.25          895.44
Permanent Ineff=
       F       F
Bank Sta=302.07,312.6
XS Rating Curve= 0 ,0
Exp/Cntr(USF)=0,0
Exp/Cntr=0.3,0.1

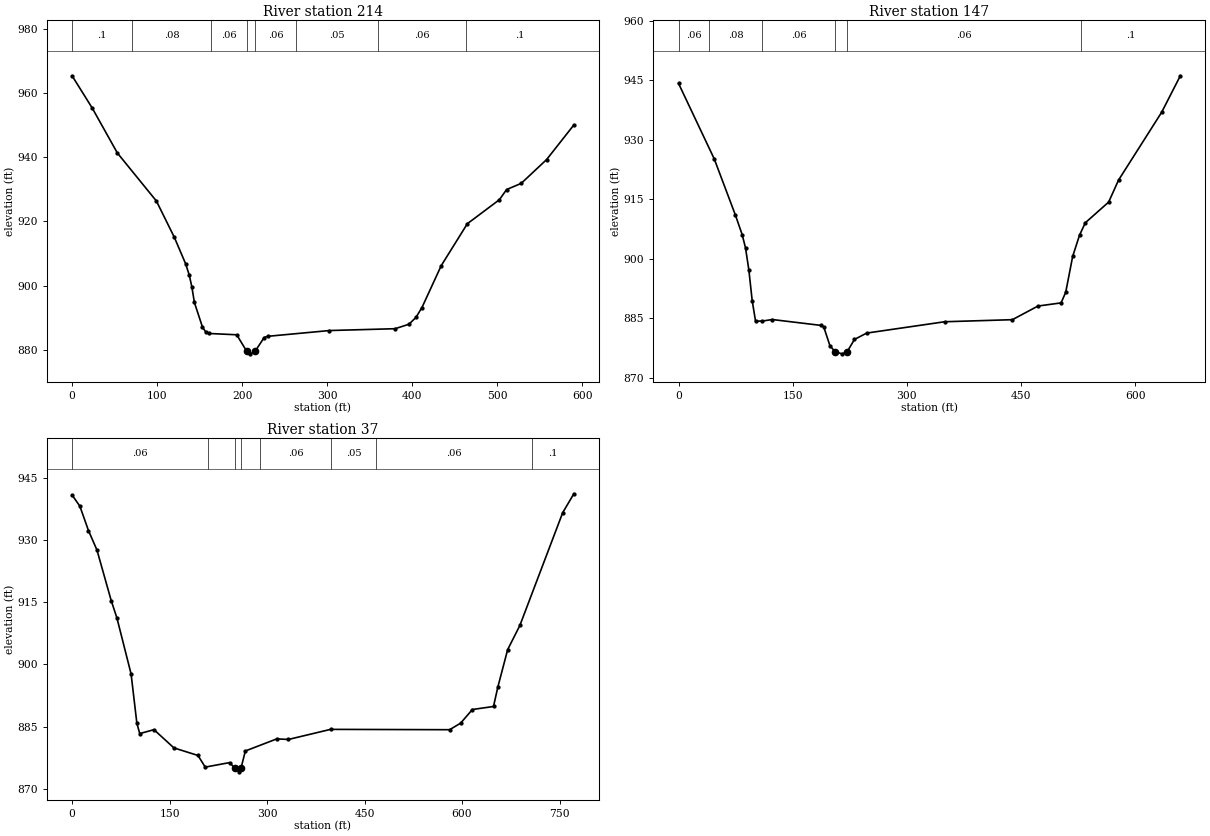
Type RM Length L Ch R = 1 ,214     ,72.6,66.3,68.8
XS GIS Cut Line= 5
 1680617.2093808368970.0291105761680557.56459899368839.044491693
1680432.42750774368854.2480635271680301.44288885368830.857953012
1680126.01705999368896.350262454
#Sta/Elev= 30
       0   965.3    23.6  955.31    53.3  941.27    99.2  926.33   120.3  915.04
   133.5  906.86   137.9  903.25   140.9  899.62   143.9  894.76   153.4  887.11
   157.6  885.44   161.5  885.11   193.7  884.71  205.25  879.66   209.9  878.78
  215.51  879.65     226  883.86     230  884.23   302.8  886.03     380   886.6
   396.3  887.99   404.5  890.11   411.6  893.19   434.3  906.24     465  919.27
   502.7  926.74   511.2  929.91   528.3  931.81   558.2  939.22590.2916     950
#Mann= 8 ,-1,0
       0      .1       0      70     .08       0  163.93     .06       0
  205.25    .045       0  215.51     .06       0  263.93     .05       0
  359.98     .06       0  463.04      .1       0
Bank Sta=205.25,215.51
XS Rating Curve= 0 ,0
Exp/Cntr(USF)=0,0
Exp/Cntr=0.3,0.1

Type RM Length L Ch R = 1 ,147     ,103.6,110.6,113.4
XS GIS Cut Line= 5
 1680658.1420742368908.6300704741680598.49729239368777.645451591
1680433.59701326368801.035562106  1680330.680527368768.289407385
1680109.64398263368864.188860496
#Sta/Elev= 30
       0  944.25    46.9  925.21    74.8  910.99    83.6   906.1      88  902.75
    92.4  897.19    96.8   889.4   101.2  884.26     110  884.27   123.2  884.66
   186.7  883.19   190.8  882.81   198.9  878.08  205.71  876.51     215     876
   221.5  876.51   231.2  879.64   247.3  881.24   349.8   884.1   438.7  884.62
   472.3  888.06   502.7  888.86   508.8  891.54   517.9  900.57     527  905.98
   534.6  909.09   565.2   914.3   578.2  919.85   634.9  936.98   659.4  946.18
#Mann= 6 ,-1,0
       0     .06       0      40     .08       0     110     .06       0
  205.71    .045       0   221.5     .06       0  528.48      .1       0
Bank Sta=205.71,221.5
XS Rating Curve= 0 ,0
Exp/Cntr(USF)=0,0
Exp/Cntr=0.3,0.1

Type RM Length L Ch R = 1 ,37      ,,,
XS GIS Cut Line= 4
1680689.19894317368903.4972406671680603.43520461368712.478004795
 1680513.7731143 368651.403827341680100.54782854368839.824162043
#Sta/Elev= 30
       0  940.85      12  938.16    25.2  932.29    38.3  927.58    60.2   915.4
      69  911.21    90.8  897.71    99.7  885.81   104.1  883.32     126  884.27
   156.7  879.87   193.7  878.05   204.9  875.24   242.4  876.33  250.42  874.97
     257   874.1   259.9  874.97   266.6  879.13     315  882.05   332.9  881.91
   397.7  884.34   580.9  884.26   597.8  885.84   615.9  889.13   648.4  889.86
   655.1  894.56   670.2  903.58     689  909.41   754.9  936.61772.0313  941.15
#Mann= 8 ,-1,0
       0     .06       0  209.39      .1       0  250.42    .045       0
   259.9      .1       0  289.39     .06       0  397.88     .05       0
  467.88     .06       0  707.88      .1       0
Bank Sta=250.42,259.9
XS Rating Curve= 0 ,0
Exp/Cntr(USF)=0,0
Exp/Cntr=0.3,0.1
LCMann Table=0

Chan Stop Cuts=-1
Use User Specified Reach Order=0
Composite Channel Slope=5